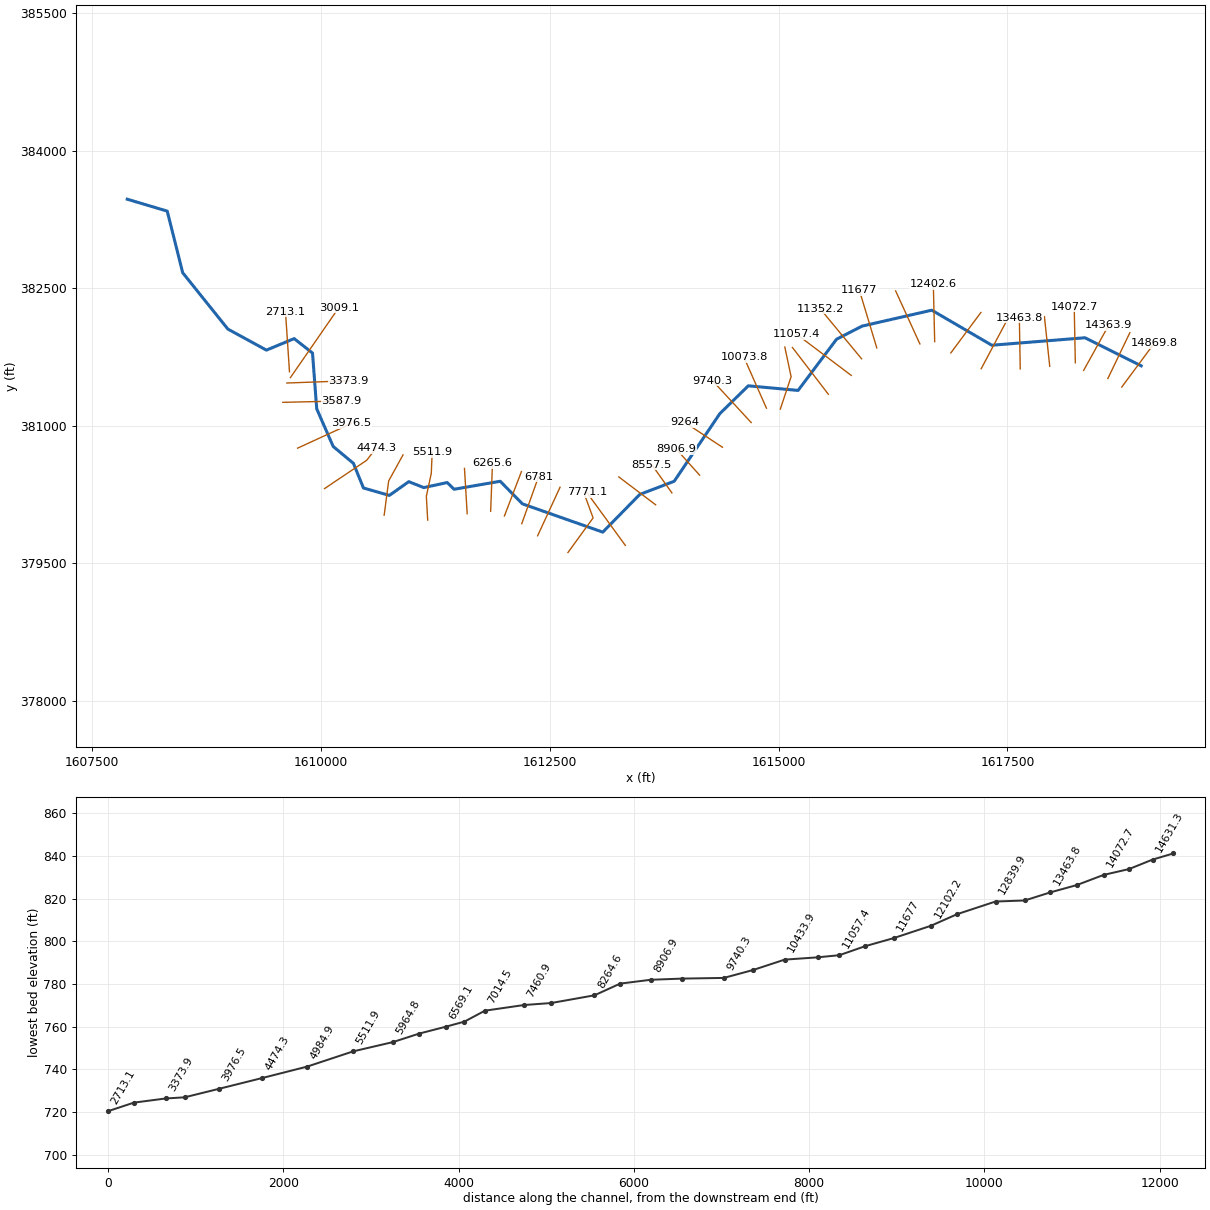
--- TROUGHFK.prj (project) ---

Proj Title=TROUGHFK
Current Plan=p01
Default Exp/Contr=0,0
English Units
Geom File=g01
Flow File=f01
Plan File=p01
BEGIN DESCRIPTION:
END DESCRIPTION:
DSS Export Rating Curves= 0
DSS Export Rating Curve Sorted= 0
DSS Export Volume Flow Curves= 0
DXF OffsetX= 0
DXF OffsetY= 0
DXF ScaleX= 0
DXF ScaleY= 0

--- TROUGHFK.p01 (plan) ---

Plan Title=Floodplain
Program Version=4.00
Geom File=g01
Flow File=f01
K Sum by GR=0
Std Step Tol=0.01
Critical Tol=0.01
Num of Std Step Trials=20
Max Error Tol=0.3
Flow Tol Ratio=0.001
Split Flow NTrial=30
Split Flow Tol=0.02
Split Flow Ratio=0.02
Log Output Level=0
Friction Slope Method=1
Unsteady Friction Slope Method=2
Unsteady Bridges Friction Slope Method=1
Global Log Level=0
CheckData=False
Run HTab=0
Run UNet=0
Run PostProcess=0
UNET Theta=0
UNET Theta Warmup=0
UNET ZTol=0
UNET ZSATol=0
UNET MxIter=0
UNET MaxInSteps=0
UNET DtIC=0
UNET DtMin=0
UNET MaxCRTS=0
UNET WFStab=0
UNET SFStab=0
UNET WFX=0
UNET SFX=0
UNET DSS MLevel=0
UNET DZMax Abort=0
UNET Convert EG Bridges=0
UNET Use Existing IB Tables=0
UNET Froude Limit=0
UNET Froude Power=0
Write IC File=0
Echo Input=False
Echo Output=False
Write Detailed=0

--- TROUGHFK.f01 (steady flow) ---

Flow Title=NFF Regression Equation
Program Version=4.00
Number of Profiles=1
Profile Names=P100yr
River Rch & RM=TROUGHFK,Main      ,14869.8
     355
River Rch & RM=TROUGHFK,Main      ,14363.9
386.5370
River Rch & RM=TROUGHFK,Main      ,14072.7
498.1372
River Rch & RM=TROUGHFK,Main      ,13463.8
502.8953
River Rch & RM=TROUGHFK,Main      ,13172.9
563.4746
River Rch & RM=TROUGHFK,Main      ,11677
577.1443
River Rch & RM=TROUGHFK,Main      ,11352.2
682.9756
River Rch & RM=TROUGHFK,Main      ,7771.1
748.4840
River Rch & RM=TROUGHFK,Main      ,7460.9
876.1611
River Rch & RM=TROUGHFK,Main      ,5964.8
940.5950
River Rch & RM=TROUGHFK,Main      ,4474.3
997.9239
River Rch & RM=TROUGHFK,Main      ,269.8
1092.973
Boundary for River Rch & Prof#=TROUGHFK,Main      ,1
Up Type=0
Dn Type=3
Dn Slope=0.009303

--- TROUGHFK.g01 (geometry) ---

Geom Title=Geometry
Program Version=4.00

River Reach=TROUGHFK        ,Main
Reach XY= 30
     1618960.799      381654.654     1618346.481      381960.631
     1617328.874      381879.132     1616672.863      382261.451
      1615911.47      382087.804     1615632.842       381945.03
     1615212.261      381386.016     1614668.513      381436.504
     1614357.027      381132.644     1613858.615      380395.017
     1613482.264       380250.94     1613078.165      379840.027
     1612200.184      380148.613      1611957.71      380394.826
     1611453.097      380307.739     1611378.898      380380.831
     1611122.311      380325.964     1610958.484      380390.733
     1610746.584      380240.523     1610463.381      380321.731
     1610353.995      380590.348     1610132.817       380774.74
     1609952.851      381185.588     1609906.946      381793.701
     1609706.434      381951.521     1609403.495      381825.763
     1608981.886       382055.55      1608488.93      382669.613
     1608319.329      383342.402     1607882.865      383472.287

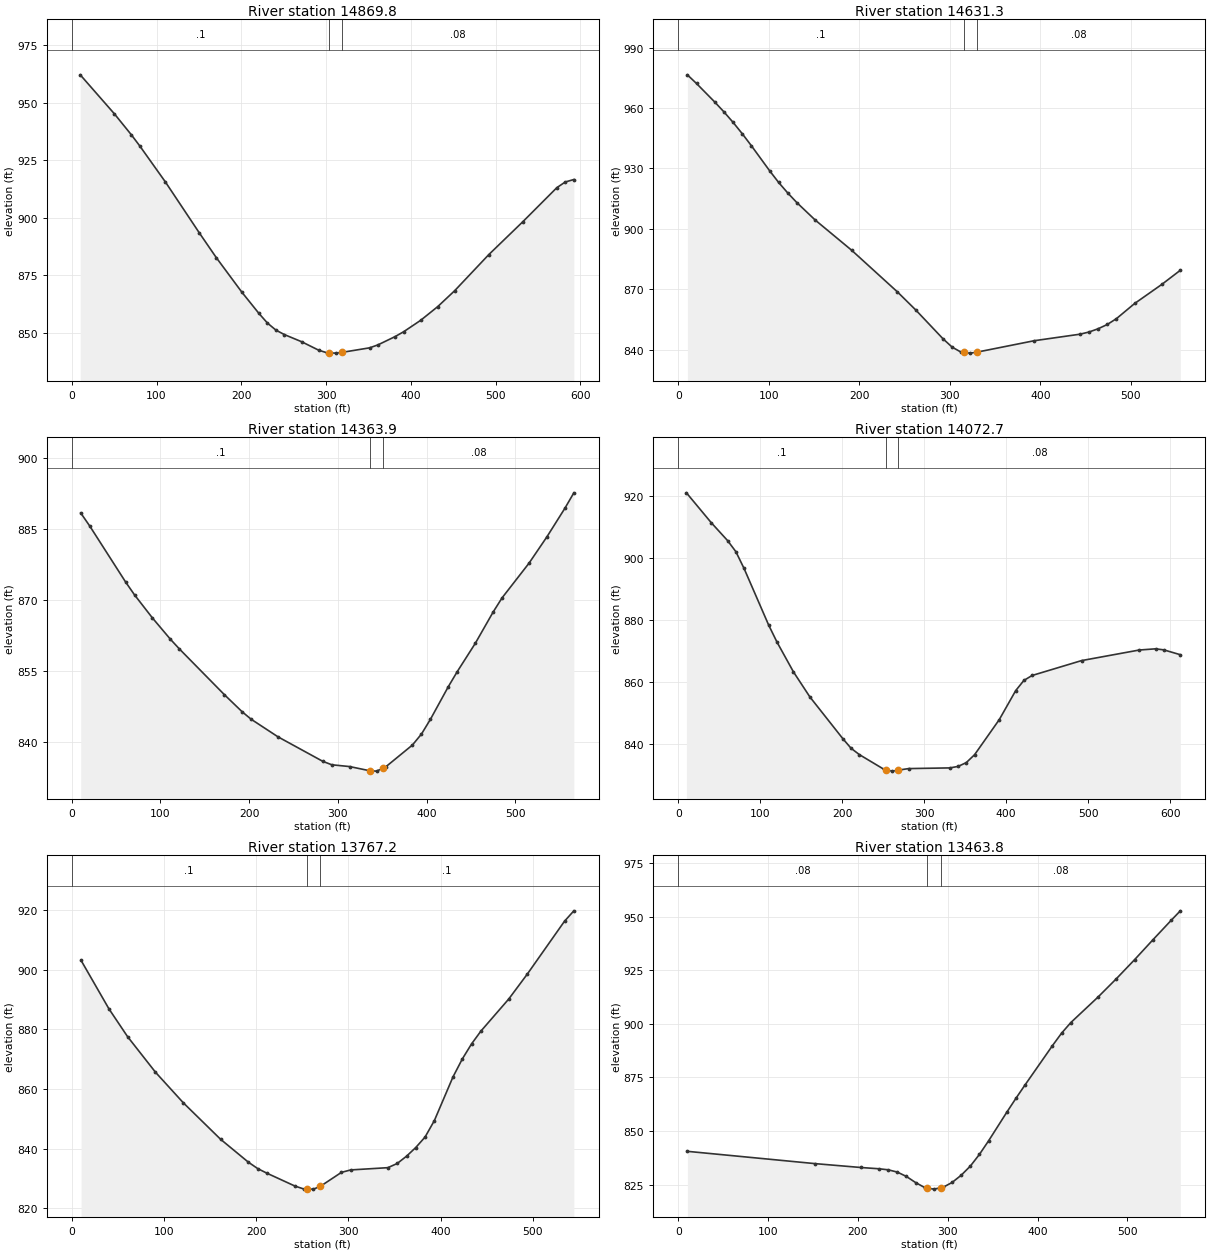
Type RM Length L Ch R = 1 ,14869.8 ,234.1,238.5,242.9
XS GIS Cut Line= 2
     1618748.675      381422.781     1619101.616      381898.271
#Sta/Elev= 30
      10  962.16    50.2  945.25    70.3   936.1    80.3  931.22   110.4  915.64
   150.6  893.41   170.6  882.68   200.7   867.7   220.8  858.49   230.8  854.32
   240.9  851.23   250.9   849.3     271  846.23   291.1  842.56   301.1  841.39
   303.6  841.36   311.1  841.26   318.6  841.58   351.3  843.56   361.3  844.87
   381.4  848.45   391.4  850.54   411.5  855.51   431.6  861.45   451.7   868.4
   491.8  884.03   531.9   898.3   572.1  913.13   582.1  915.61   592.2  916.68
#Mann= 3 , 0 , 0
       0      .1       0   303.6    .045       0   318.6     .08       0
Bank Sta=303.6,318.6
XS Rating Curve= 0 ,0
Exp/Cntr=0.3,0.1

Type RM Length L Ch R = 1 ,14631.3 ,269.1,267.4,265.7
XS GIS Cut Line= 2
     1618596.715      381515.918     1618836.911      382015.918
#Sta/Elev= 30
    10.1  976.46    20.2  972.16    40.3  962.99    50.4  958.12    60.5  952.93
    70.6  947.31    80.7  941.35   100.9   928.9   110.9  923.07     121  917.83
   131.1  913.03   151.3  904.41   191.6  889.41   242.1  868.77   262.2  859.87
   292.5  845.49   302.6  841.34   312.7  838.79   315.2  838.68   322.7  838.36
   330.2  838.86   393.3  844.52   443.8  847.75   453.8  848.83   463.9  850.45
     474  852.57   484.1  855.46   504.3  863.01   534.5  872.54   554.7  879.47
#Mann= 3 , 0 , 0
       0      .1       0   315.2    .045       0   330.2     .08       0
Bank Sta=315.2,330.2
XS Rating Curve= 0 ,0
Exp/Cntr=0.3,0.1

Type RM Length L Ch R = 1 ,14363.9 ,279.3,291.2,303.2
XS GIS Cut Line= 2
     1618332.009      381604.153     1618606.518      382099.251
#Sta/Elev= 30
    10.1  888.42    20.2  885.68    60.7  873.85    70.8  871.12      91  866.25
   111.2  861.77   121.3  859.73   171.9   850.1   192.1  846.46   202.2  844.89
   232.5  841.17   283.1  835.99   293.2  835.27   313.4  834.89   336.2     834
   343.7  833.93   351.2  834.58   353.8   834.8   384.1  839.44   394.3  841.76
   404.4  844.87   424.6  851.77   434.7  854.95   454.9  860.88   475.1  867.51
   485.2  870.51   515.6  877.83   535.8   883.4     556  889.41   566.1  892.67
#Mann= 3 , 0 , 0
       0      .1       0   336.2    .045       0   351.2     .08       0
Bank Sta=336.2,351.2
XS Rating Curve= 0 ,0
Exp/Cntr=0.3,0.1

Type RM Length L Ch R = 1 ,14072.7 ,303.5,305.5,307.4
XS GIS Cut Line= 2
     1618241.283      381687.891     1618229.067      382300.232
#Sta/Elev= 30
      10  920.96    40.2  911.35    60.2  905.55    70.3  901.98    80.3  896.56
   110.4  878.24   120.5  872.79   140.6  863.17   160.6  855.11   200.8  841.64
   210.8  838.56   220.9  836.51     251  831.75   253.6   831.6     261  831.17
   268.6   831.5   281.1  831.99   331.3  832.21   341.4  832.69   351.4  833.92
   361.5  836.46   391.6  847.77   411.7  857.15   421.7  860.44   431.7  862.03
     492  866.83   562.3  870.24   582.3  870.63   592.4  870.29   612.5  868.73
#Mann= 3 , 0 , 0
       0      .1       0   253.6    .045       0   268.6     .08       0
Bank Sta=253.6,268.6
XS Rating Curve= 0 ,0
Exp/Cntr=0.3,0.1

Type RM Length L Ch R = 1 ,13767.2 ,304.8,303.4,302
XS GIS Cut Line= 2
     1617961.543      381649.926     1617903.596      382191.423
#Sta/Elev= 30
    10.1  903.05    40.3  886.83    60.5  877.52    90.8  865.59     121  855.34
   161.4  843.13   191.6  835.44   201.7   833.3   211.8  831.74     242  827.46
   252.1  826.42   254.7  826.42   262.2  826.42   269.7  827.37   292.5  832.03
   302.5  832.85   342.9  833.61     353  835.01   363.1  837.45   373.1  840.35
   383.2  843.86   393.3  849.38   413.5  864.01   423.6  870.02   433.7   875.1
   443.7  879.33     474  890.12   494.2   898.5   534.5  916.19   544.6  919.66
#Mann= 3 , 0 , 0
       0      .1       0   254.7    .045       0   269.7      .1       0
Bank Sta=254.7,269.7
XS Rating Curve= 0 ,0
Exp/Cntr=0.3,0.1

Type RM Length L Ch R = 1 ,13463.8 ,303.4,290.9,277
XS GIS Cut Line= 2
     1617639.394      381620.857      1617629.59      382179.681
#Sta/Elev= 30
    10.2  840.58   152.4  834.85   203.2  833.05   223.6  832.45   233.7  831.97
   243.9  830.91     254  828.87   264.2  826.04   274.4  823.69     277  823.51
   284.5  822.97     292  823.58   294.7   823.8   304.9  826.09     315  829.45
   325.2  833.72   335.3  839.17   345.5  845.49   365.8  858.84     376  865.34
   386.2  871.61   416.6  889.85   426.8  895.68     437  900.57   467.5  912.55
   487.8  921.05   508.1  929.93   528.4  939.15   548.7  948.21   558.9  952.65
#Mann= 3 , 0 , 0
       0     .08       0     277    .045       0     292     .08       0
Bank Sta=277,292
XS Rating Curve= 0 ,0
Exp/Cntr=0.3,0.1

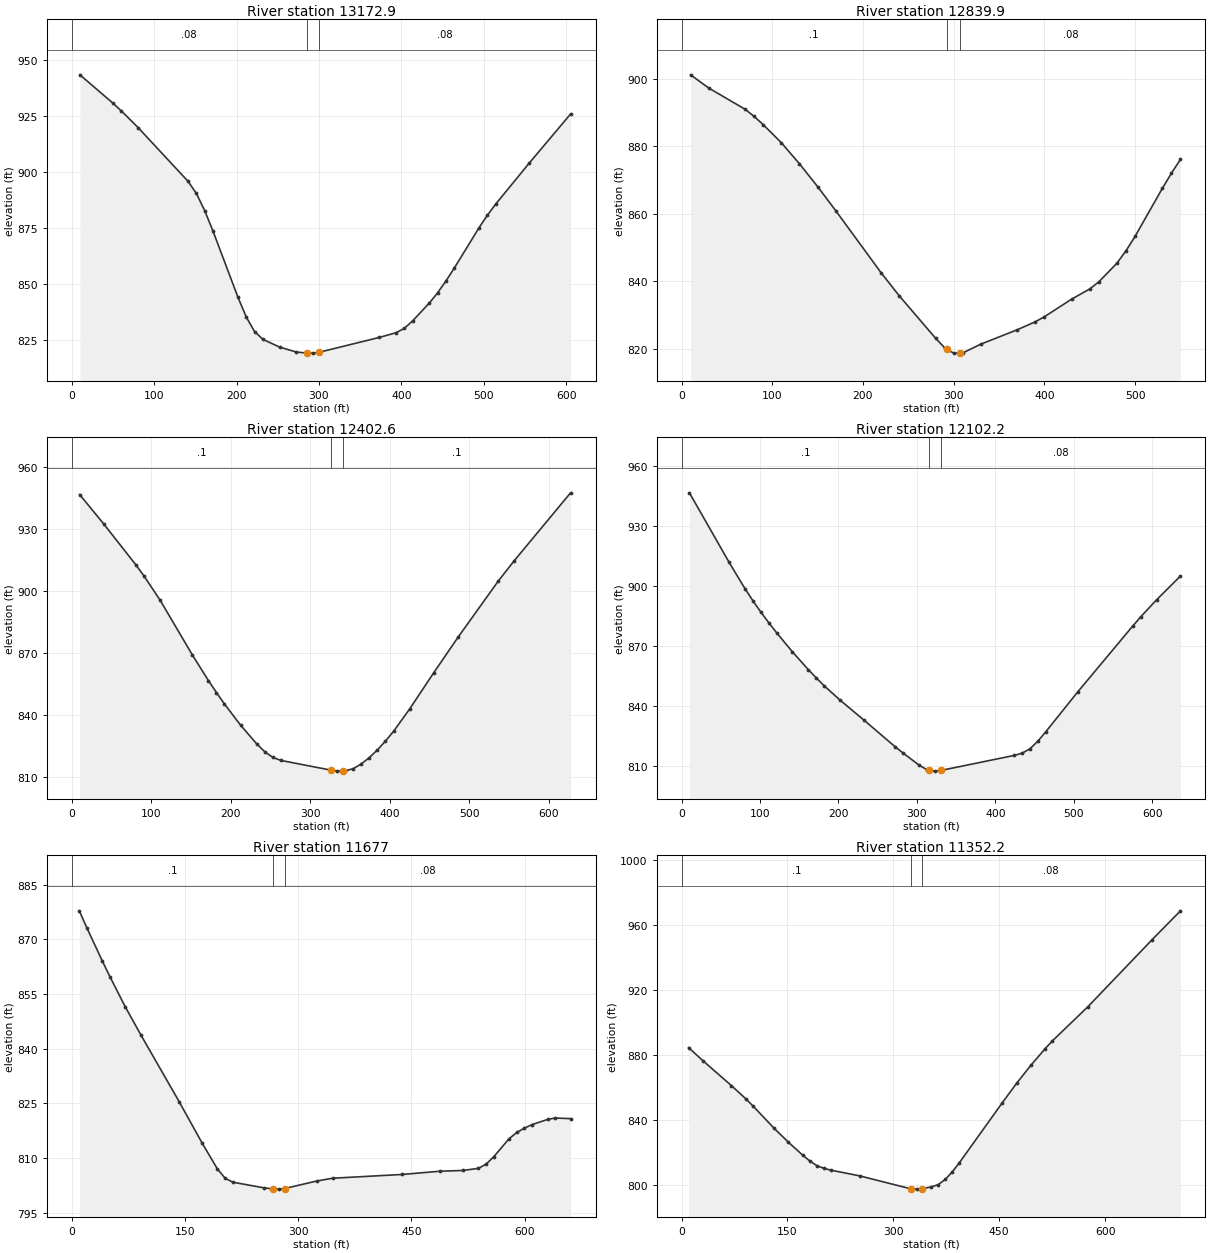
Type RM Length L Ch R = 1 ,13172.9 ,336.1,333,331.2
XS GIS Cut Line= 2
     1617212.737      381622.669     1617497.051      382156.982
#Sta/Elev= 30
    10.1  943.57    50.4  930.81    60.5  927.38    80.7  919.97   141.2  895.99
   151.3  890.57   161.4  882.89   171.5  873.72   201.7  844.22   211.8  835.36
   221.9  828.83     232  825.35   252.2   821.9   272.4   819.7     285  819.22
   292.5  819.19     300  819.56   373.2   826.2   393.4   828.3   403.5  830.24
   413.6  833.59   433.8  841.54   443.8  846.09   453.9  851.35     464  857.08
   494.3  875.31   504.4  880.85   514.5  885.85   554.8     904   605.2  926.05
#Mann= 3 , 0 , 0
       0     .08       0     285    .045       0     300     .08       0
Bank Sta=285,300
XS Rating Curve= 0 ,0
Exp/Cntr=0.3,0.1

Type RM Length L Ch R = 1 ,12839.9 ,422.3,437.3,452.3
XS GIS Cut Line= 2
     1616881.028      381795.329      1617209.46      382236.506
#Sta/Elev= 30
      10  901.11      30   897.2      70  890.93      80   888.8      90  886.37
     110  881.02     130  874.77     150  868.02     170  860.88     220   842.5
     240  835.67     280  823.13     290  820.28   292.5  819.88     300   818.7
   307.5  818.74     310  818.76     330  821.37     370  825.61     390  827.99
     400  829.47     430  834.68     450   837.7     460  839.81     480  845.34
     490  849.03     500  853.29     530  867.48     540  871.95     550   876.1
#Mann= 3 , 0 , 0
       0      .1       0   292.5    .045       0   307.5     .08       0
Bank Sta=292.5,307.5
XS Rating Curve= 0 ,0
Exp/Cntr=0.3,0.1

Type RM Length L Ch R = 1 ,12402.6 ,291.3,300.4,309.5
XS GIS Cut Line= 2
     1616704.558      381917.879     1616689.852       382545.33
#Sta/Elev= 30
    10.1  946.87    40.5  932.57      81  912.69    91.1  907.36   111.4   895.6
   151.8  869.16   172.1  856.68   182.2  850.88   192.3  845.31   212.6  835.03
   232.8  826.01     243  822.17   253.1  819.44   263.2  817.97   326.6  813.24
   334.1  812.78   341.6  812.84   344.2  812.86   354.3     814   364.4  816.27
   374.5  819.35   384.7   823.1   394.8  827.35   404.9  832.05   425.2  842.91
   455.5  860.48   485.9  877.59   536.5  904.84   556.8  914.82   627.6   947.7
#Mann= 3 , 0 , 0
       0      .1       0   326.6    .045       0   341.6      .1       0
Bank Sta=326.6,341.6
XS Rating Curve= 0 ,0
Exp/Cntr=0.3,0.1

Type RM Length L Ch R = 1 ,12102.2 ,428.2,425.1,422.1
XS GIS Cut Line= 2
     1616542.793      381893.369     1616278.087        382471.8
#Sta/Elev= 30
    10.1  946.61    60.6  911.88    80.8  898.72    90.9  892.66     101     887
   111.1  881.67   121.2   876.6   141.4  867.03   161.6  858.15   171.7  854.02
   181.7  850.11   201.9  842.93   232.2  832.99   272.6  819.43   282.7  816.31
   302.9   810.3     313  808.02   315.6  807.84   323.1  807.32   330.6  807.65
   424.1  815.18   434.2  816.29   444.3   818.5   454.4  822.36   464.5  827.07
   504.9  846.86   575.5  880.06   585.6  884.63   605.8  893.13   636.1  904.98
#Mann= 3 , 0 , 0
       0      .1       0   315.6    .045       0   330.6     .08       0
Bank Sta=315.6,330.6
XS Rating Curve= 0 ,0
Exp/Cntr=0.3,0.1

Type RM Length L Ch R = 1 ,11677   ,315.8,324.9,333.9
XS GIS Cut Line= 2
     1616072.205      381849.251     1615881.028      382481.604
#Sta/Elev= 30
    10.2  877.81    20.3  873.09    40.7  864.04    50.8  859.73    71.1  851.47
    91.5  843.87   142.3  825.53   172.8  814.15   193.1  807.04   203.3  804.52
   213.4  803.43   254.1   801.9   266.9  801.59   274.4  801.53   281.9  801.69
   325.2  803.78   345.6  804.52     437  805.54   487.8  806.44   518.3  806.65
   538.7  807.23   548.8  808.37     559  810.43   579.3  815.37   589.5  817.07
   599.6  818.26   609.8  819.23   630.1  820.63   640.3  821.02   660.6  820.85
#Mann= 3 , 0 , 0
       0      .1       0   266.9    .045       0   281.9     .08       0
Bank Sta=266.9,281.9
XS Rating Curve= 0 ,0
Exp/Cntr=0.3,0.1

Type RM Length L Ch R = 1 ,11352.2 ,289.5,294.7,299.9
XS GIS Cut Line= 2
     1615905.538      381731.604     1615454.558      382275.722
#Sta/Elev= 30
    10.1  884.55    30.3  876.54    70.7  861.26    90.9  853.24     101  848.87
   131.2  835.06   151.4  826.52   171.6  818.61   181.7  815.01   191.8  812.13
   201.9  810.47     212  809.35   252.4  805.88   323.1  798.12   325.7  798.02
   333.2  797.75   340.7  798.03   353.4  799.06   363.5   800.5   373.5  803.67
   383.6  808.37   393.7  814.05   454.3  850.72   474.5  862.61   494.7  873.67
   514.9  883.88     525  888.58   575.5  909.64   666.3   950.7   706.7  968.51
#Mann= 3 , 0 , 0
       0      .1       0   325.7    .045       0   340.7     .08       0
Bank Sta=325.7,340.7
XS Rating Curve= 0 ,0
Exp/Cntr=0.3,0.1

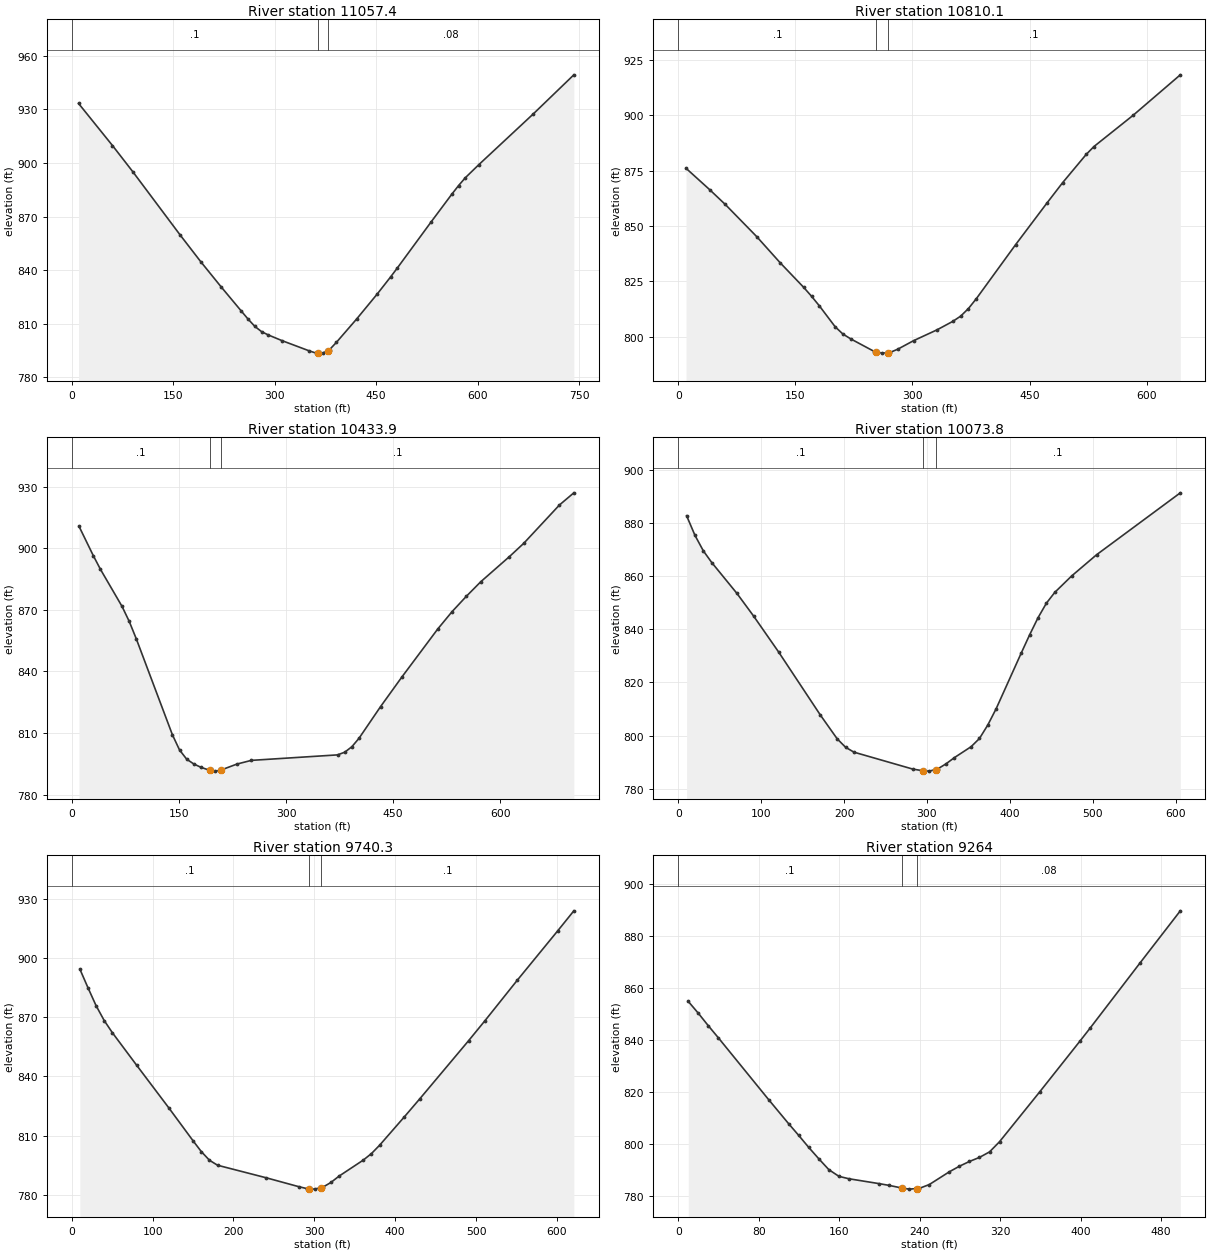
Type RM Length L Ch R = 1 ,11057.4 ,253.9,247.3,240.7
XS GIS Cut Line= 2
     1615792.793      381550.231     1615199.656       381996.31
#Sta/Elev= 30
      10  933.38    60.2  909.78    90.3  895.09   160.5  859.55   190.6  844.77
   220.6  830.73   250.7  817.06   260.8  812.51   270.8  808.45   280.8   805.5
   290.8  803.66   310.9  800.51     351   794.8     361  793.56   363.6  793.55
   371.1  793.53   378.6     795   381.1  795.49   391.1  799.52   421.2  812.68
   451.3  826.52   471.4  836.24   481.4  841.28   531.5  867.16   561.6  882.43
   571.7  887.32   581.7  891.72   601.7  899.07     682  927.41   742.2  949.39
#Mann= 3 , 0 , 0
       0      .1       0   363.6    .045       0   378.6     .08       0
Bank Sta=363.6,378.6
XS Rating Curve= 0 ,0
Exp/Cntr=0.3,0.1

Type RM Length L Ch R = 1 ,10810.1 ,397.9,376.2,354.6
XS GIS Cut Line= 2
     1615542.793      381344.349     1615150.636      381854.153
#Sta/Elev= 30
      10  876.02    40.2  866.39    60.3  859.68   100.5  845.17   130.6  833.34
   160.8  822.21   170.8   818.2   180.9  813.84     201  804.45     211  801.14
   221.1  798.94   251.2  793.26   253.8  793.07   261.3  792.53   268.8  792.75
   271.3  792.82   281.4  794.34   301.5  798.16   331.6  803.06   351.7  806.87
   361.8  809.23   371.8  812.68   381.9  817.13   432.1  841.48   472.3   860.3
   492.4  869.51   522.6  882.27   532.6  885.86   582.9     900   643.2  918.24
#Mann= 3 , 0 , 0
       0      .1       0   253.8    .045       0   268.8      .1       0
Bank Sta=253.8,268.8
XS Rating Curve= 0 ,0
Exp/Cntr=0.3,0.1

Type RM Length L Ch R = 1 ,10433.9 ,343.3,360.1,377
XS GIS Cut Line= 3
     1615018.283      381182.584      1615135.93      381535.526
     1615067.303      381859.055
#Sta/Elev= 30
    10.1  910.71    30.2  896.35    40.2   889.7    70.4  871.65    80.4  864.39
    90.5  855.72   140.8  809.22   150.8  801.78   160.9  797.25   170.9  794.92
     181  793.28   193.6   791.8   201.1  791.45   208.6  791.95   231.3   794.9
   251.4  796.69     372  799.36   382.1  800.67   392.1  803.34   402.1  807.46
   432.2  822.85   462.2  837.34   512.3  860.68   532.4  869.15   552.4  876.62
   572.5  883.68   612.6  895.92   632.6  902.37   682.7  921.09   702.8  926.99
#Mann= 3 , 0 , 0
       0      .1       0   193.6    .045       0   208.6      .1       0
Bank Sta=193.6,208.6
XS Rating Curve= 0 ,0
Exp/Cntr=0.3,0.1

Type RM Length L Ch R = 1 ,10073.8 ,326.1,333.5,340.9
XS GIS Cut Line= 2
     1614866.322      381192.388     1614621.224       381746.31
#Sta/Elev= 30
    10.1  882.78    20.2  875.37    30.3  869.54    40.4  865.16    70.7  853.57
    90.9     845   121.1  831.46   171.6  807.65   191.8  798.74   201.9  795.57
     212  793.73   282.7  787.38   295.4  786.71   302.9  786.59   310.4   787.2
     313  787.41   323.1  789.35   333.1  791.66   353.3  795.79   363.4  798.89
   373.5  803.98   383.6  810.14   413.9  831.13     424  837.97   434.1  844.39
   444.2  849.86   454.3  853.92   474.5  860.06   504.8  868.11   605.7   891.4
#Mann= 3 , 0 , 0
       0      .1       0   295.4    .045       0   310.4      .1       0
Bank Sta=295.4,310.4
XS Rating Curve= 0 ,0
Exp/Cntr=0.3,0.1

Type RM Length L Ch R = 1 ,9740.3  ,470.8,476.3,481.7
XS GIS Cut Line= 2
     1614699.656      381035.526     1614278.087      381491.408
#Sta/Elev= 30
      10  894.27      20  884.86      30  875.81    40.1  868.23    50.1  862.13
    80.1  845.67   120.2  823.91   150.2  807.24   160.2  801.88   170.3  797.49
   180.3  794.97   240.4  788.63   280.4  784.16   290.4  783.18   292.9   783.1
   300.4  782.88   307.9  783.61   310.5  783.86   320.5  786.26   330.5  789.45
   360.5  797.58   370.6  800.88   380.6  805.06   410.6  819.14   430.6   828.7
   490.7     858   510.8  868.05   550.8  888.56   600.9  913.61   620.9  923.76
#Mann= 3 , 0 , 0
       0      .1       0   292.9    .045       0   307.9      .1       0
Bank Sta=292.9,307.9
XS Rating Curve= 0 ,0
Exp/Cntr=0.3,0.1

Type RM Length L Ch R = 1 ,9264    ,362.8,357,351.3
XS GIS Cut Line= 2
      1614385.93      380765.918     1613969.264      381040.428
#Sta/Elev= 30
      10   854.9      20  850.33    29.9  845.53    39.9  840.87    89.8  817.08
   109.8  807.74   119.8  803.24   129.7  798.64   139.7  794.26   149.7  790.06
   159.7  787.49   169.6  786.56   199.6  784.68   209.6     784     222  783.01
   229.5  782.56     237  782.77   239.5  782.84   249.5  784.32   269.4  789.23
   279.4  791.38   289.4  793.22   299.4  794.79   309.4  796.91   319.3  800.82
   359.3  820.06   399.2  839.58   409.2  844.54     459  869.75     499  889.82
#Mann= 3 , 0 , 0
       0      .1       0     222    .045       0     237     .08       0
Bank Sta=222,237
XS Rating Curve= 0 ,0
Exp/Cntr=0.3,0.1

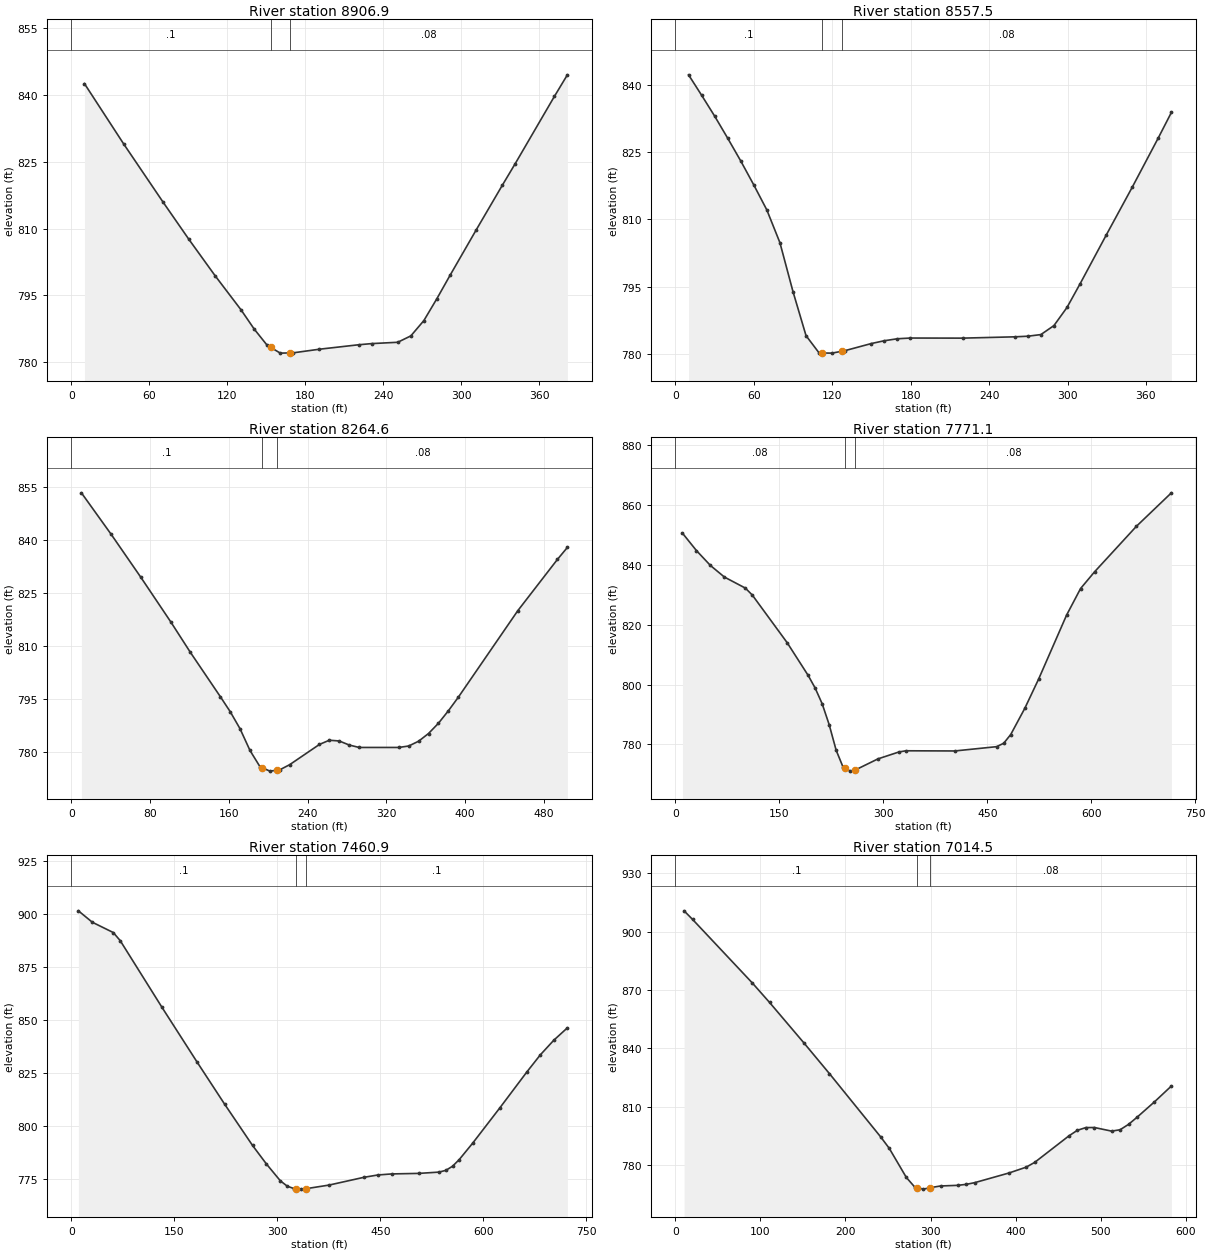
Type RM Length L Ch R = 1 ,8906.9  ,351.7,349.4,347.1
XS GIS Cut Line= 2
      1614135.93      380461.996     1613881.028       380746.31
#Sta/Elev= 25
      10  842.57    40.2  829.02    70.3  816.04    90.4  807.58   110.5  799.44
   130.6  791.72   140.7  787.41   150.7  783.76   153.3  783.31   160.8  782.01
   168.3  782.06   170.8  782.08   190.9  782.89   221.1  783.89   231.1  784.15
   251.2  784.45   261.3  785.89   271.3  789.32   281.4  794.28   291.4  799.46
   311.5  809.65   331.6  819.68   341.7  824.62   371.8   839.7   381.8  844.55
#Mann= 3 , 0 , 0
       0      .1       0   153.3    .045       0   168.3     .08       0
Bank Sta=153.3,168.3
XS Rating Curve= 0 ,0
Exp/Cntr=0.3,0.1

Type RM Length L Ch R = 1 ,8557.5  ,286,292.9,299.8
XS GIS Cut Line= 2
     1613833.662      380268.289     1613613.073      380577.113
#Sta/Elev= 30
      10  842.19      20  837.64      30  832.98    39.9   828.1    49.9  823.03
    59.9  817.68    69.9   812.1    79.9  804.82    89.9  793.93    99.9   784.1
   109.9  780.25   112.3  780.24   119.8  780.21   127.3  780.63   129.8  780.77
   149.8  782.34   159.8  782.97   169.8  783.41   179.8  783.57   219.7  783.55
   259.7  783.84   269.7  783.98   279.6  784.34   289.6  786.34   299.6  790.38
   309.6  795.64   329.6  806.49   349.6   817.2   369.5  828.16   379.5  833.82
#Mann= 3 , 0 , 0
       0      .1       0   112.3    .045       0   127.3     .08       0
Bank Sta=112.3,127.3
XS Rating Curve= 0 ,0
Exp/Cntr=0.3,0.1

Type RM Length L Ch R = 1 ,8264.6  ,500.5,493.5,486.5
XS GIS Cut Line= 2
     1613655.538      380138.467     1613253.577      380442.388
#Sta/Elev= 30
    10.1  853.37    40.3  841.66    70.5   829.5   100.8  816.95   120.9  808.26
   151.2   795.8   161.3  791.53   171.3   786.7   181.4  780.57   191.5     776
   194.1  775.67   201.6  774.73   209.1     775   211.6  775.09   221.7  776.55
     252  782.28     262  783.46   272.1  783.25   282.2  782.11   292.3  781.42
   332.6  781.42   342.7  781.83   352.7  783.18   362.8  785.36   372.9  788.26
     383  791.79   393.1  795.62   453.5  820.06   493.8  834.56   503.9  837.94
#Mann= 3 , 0 , 0
       0      .1       0   194.1    .045       0   209.1     .08       0
Bank Sta=194.1,209.1
XS Rating Curve= 0 ,0
Exp/Cntr=0.3,0.1

Type RM Length L Ch R = 1 ,7771.1  ,341.5,310.2,277.7
XS GIS Cut Line= 2
     1613324.576      379695.479     1612903.008       380273.91
#Sta/Elev= 30
    10.1  850.52    30.2  844.73    50.4  839.75    70.6  835.88   100.8   832.2
   110.9  829.87   161.3  813.94   191.5  803.05   201.6  798.83   211.7   793.6
   221.8  786.64   231.9  778.08   241.9  772.43   244.5  772.09     252  771.11
   259.5  771.49   292.3   775.2   322.6  777.51   332.7   777.9   403.2  777.84
   463.7  779.28   473.8  780.43   483.9  783.33   504.1  792.03   524.2  801.86
   564.5  823.18   584.7  832.05   604.9  837.63   665.3  852.82   715.8  863.99
#Mann= 3 , 0 , 0
       0     .08       0   244.5    .045       0   259.5     .08       0
Bank Sta=244.5,259.5
XS Rating Curve= 0 ,0
Exp/Cntr=0.3,0.1

Type RM Length L Ch R = 1 ,7460.9  ,439.8,446.4,454.2
XS GIS Cut Line= 3
     1612698.031      379617.767     1612972.541      379995.218
     1612884.306      380235.414
#Sta/Elev= 30
    10.1   901.6    30.4  896.21    60.9  891.35      71  887.54   131.9  856.02
   182.6   830.4   223.2  810.28   263.8  790.82   284.1  782.04   304.4  774.08
   314.5  771.55   324.7  770.37   327.3  770.32   334.8  770.17   342.3   770.4
   375.4  772.09   426.1  775.75   446.4  776.85   466.7  777.35   506.1   777.6
   535.6  778.21   545.5  779.04   555.3  780.99   565.1  784.16   584.8  791.96
   624.2  808.55   663.6  825.53   683.2  833.59   702.9  840.53   722.6  846.33
#Mann= 3 , 0 , 0
       0      .1       0   327.3    .045       0   342.3      .1       0
Bank Sta=327.3,342.3
XS Rating Curve= 0 ,0
Exp/Cntr=0.3,0.1

Type RM Length L Ch R = 1 ,7014.5  ,231.4,233.4,235.5
XS GIS Cut Line= 2
     1612366.322      379800.231      1612611.42      380329.643
#Sta/Elev= 30
    10.1  910.72    20.1   906.3    90.5  873.55   110.6  863.61   150.9  842.85
   181.1  826.96   241.4  794.39   251.5  788.49   271.6  773.51   281.6  768.51
   284.2  768.25   291.7  767.52   299.2  768.23   311.8  769.14   331.9  769.47
     342  769.97     352  770.85   392.3  775.82   412.4   778.8   422.5  781.26
   462.7  794.88   472.8   797.8   482.8  799.19   492.9  799.22     513  797.37
     523  798.06   533.1  800.88   543.2  804.59   563.3  812.36   583.4  820.58
#Mann= 3 , 0 , 0
       0      .1       0   284.2    .045       0   299.2     .08       0
Bank Sta=284.2,299.2
XS Rating Curve= 0 ,0
Exp/Cntr=0.3,0.1

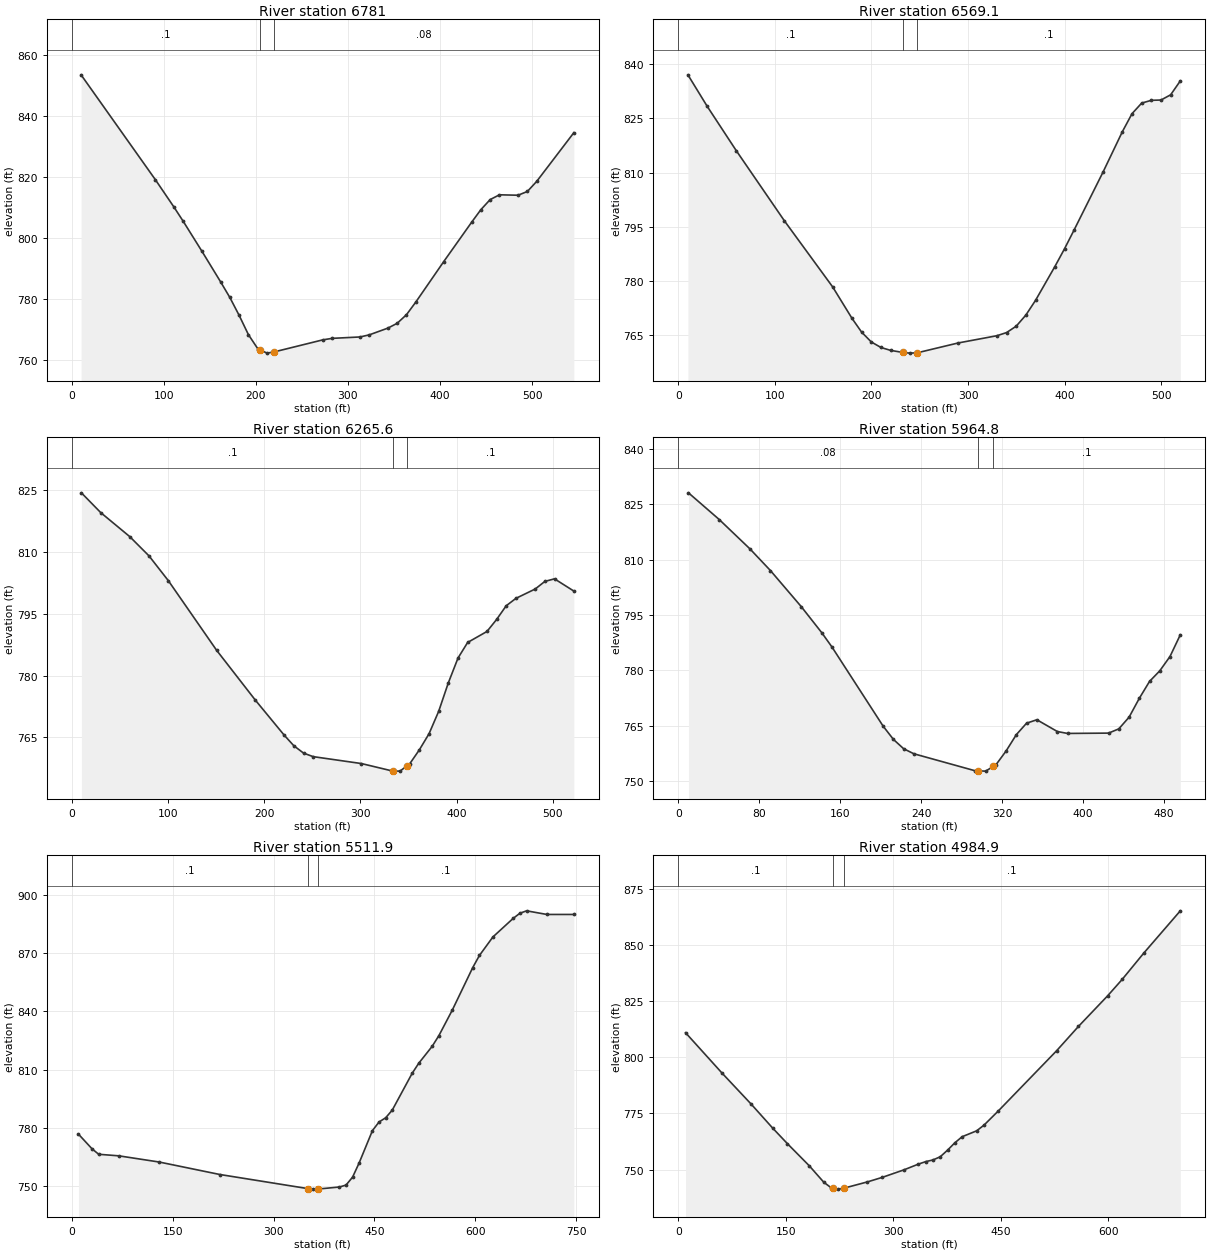
Type RM Length L Ch R = 1 ,6781    ,211.3,211.9,212.5
XS GIS Cut Line= 2
     1612192.903      379931.523     1612376.732      380445.046
#Sta/Elev= 30
    10.1  853.62    90.9  819.21   111.1  810.23   121.2  805.54   141.4  795.78
   161.6   785.8   171.7  780.64   181.8  774.78   191.9  768.44     202  763.86
   204.6  763.48   212.1  762.39   219.6  762.77   272.7  766.74   282.8  767.23
   313.1  767.69   323.2  768.38   343.4  770.59   353.5  772.17   363.6  774.99
   373.7  779.12     404  792.37   434.3  805.27   444.4  809.42   454.5  812.73
   464.6  814.29   484.8  814.15   494.9  815.38     505  818.67   545.4  834.66
#Mann= 3 , 0 , 0
       0      .1       0   204.6    .045       0   219.6     .08       0
Bank Sta=204.6,219.6
XS Rating Curve= 0 ,0
Exp/Cntr=0.3,0.1

Type RM Length L Ch R = 1 ,6569.1  ,297,303.5,310
XS GIS Cut Line= 2
     1612003.577      380015.918     1612189.852      380501.212
#Sta/Elev= 30
      10  837.09      30  828.36      60  816.12     110  796.62   159.9  778.34
   179.9  769.64   189.9  765.81   199.9   763.1   209.9  761.57   219.9  760.77
   232.4  760.21   239.9  760.01   247.4   760.1   289.9  762.83   329.9  764.83
   339.9   765.7   349.9  767.47   359.9  770.55   369.9  774.62   389.9  783.97
   399.9   788.9   409.9  794.15   439.8  810.16   459.8  821.34   469.8  826.33
   479.8  829.26   489.8  830.03   499.8  830.11   509.8  831.56   519.8  835.41
#Mann= 3 , 0 , 0
       0      .1       0   232.4    .045       0   247.4      .1       0
Bank Sta=232.4,247.4
XS Rating Curve= 0 ,0
Exp/Cntr=0.3,0.1

Type RM Length L Ch R = 1 ,6265.6  ,298.9,300.8,302.8
XS GIS Cut Line= 2
     1611853.218      380067.397       1611873.2      380588.912
#Sta/Elev= 30
      10  824.38    30.1  819.58    60.2  813.76    80.3  809.06   100.4  803.04
   150.5  786.16   190.7  774.07   220.8  765.53   230.8  762.96   240.9  761.17
   250.9  760.31   301.1  758.63   333.7   756.8   341.2  756.79   348.7  758.12
   351.3  758.57   361.3  761.96   371.4  765.88   381.4  771.32   391.4  778.21
   401.5  784.26   411.5  788.04   431.6  790.71   441.6  793.62   451.6  796.95
   461.7  798.75   481.8  801.03   491.8  802.87   501.8  803.49   521.9  800.52
#Mann= 3 , 0 , 0
       0      .1       0   333.7    .045       0   348.7      .1       0
Bank Sta=333.7,348.7
XS Rating Curve= 0 ,0
Exp/Cntr=0.3,0.1

Type RM Length L Ch R = 1 ,5964.8  ,459,452.9,446.8
XS GIS Cut Line= 2
     1611596.715      380040.428     1611567.303      380535.526
#Sta/Elev= 30
    10.1  828.04    40.5  820.82    70.9  812.87    91.1  807.02   121.5  797.28
   141.7  790.25   151.8  786.38   202.4  764.96   212.6  761.36   222.7  758.84
   232.8  757.48   293.5  752.87   296.2  752.85   303.7  752.79   311.2  754.05
   313.8  754.48   323.9  758.24     334  762.65   344.1  765.75   354.3  766.68
   374.5   763.5   384.6  762.98   425.1  763.07   435.2  764.21   445.4  767.38
   455.5  772.48   465.6  777.05   475.7  779.91   485.8  783.78     496  789.66
#Mann= 3 , 0 , 0
       0     .08       0   296.2    .045       0   311.2      .1       0
Bank Sta=296.2,311.2
XS Rating Curve= 0 ,0
Exp/Cntr=0.3,0.1

Type RM Length L Ch R = 1 ,5511.9  ,524.7,527,529.3
XS GIS Cut Line= 4
     1611165.342        379971.8     1611150.636      380231.604
     1611204.558      380481.604     1611214.362      380711.996
#Sta/Elev= 30
      10  776.75      30  769.26      40   766.4    70.1  765.59   130.1   762.4
   220.2  755.98   351.1  748.72   358.6  748.45   366.1  748.49   397.9  749.54
   407.8  750.53   417.6  754.63   427.4     762   447.1  778.58   456.9  783.03
   466.8   785.2   476.6  789.16   506.1  808.05     516  813.29     536  822.03
     546  827.56   566.1  840.82   596.2  862.51   606.2  868.79   626.3  878.33
   656.3  887.85   666.4  890.53   676.4  891.77   706.5   889.9   746.6   889.9
#Mann= 3 , 0 , 0
       0      .1       0   351.1    .045       0   366.1      .1       0
Bank Sta=351.1,366.1
XS Rating Curve= 0 ,0
Exp/Cntr=0.3,0.1

Type RM Length L Ch R = 1 ,4984.9  ,529.4,510.6,491.8
XS GIS Cut Line= 3
     1610689.852      380025.722     1610738.871      380398.271
     1610895.734      380682.584
#Sta/Elev= 30
    10.2  810.93    60.9  793.02   101.6  779.19     132  768.37   152.3  761.53
   182.8  751.68   203.1  744.34   213.3   741.9   215.9  741.74   223.4  741.28
   230.9  741.68     264   744.5   284.4  746.49   314.8  749.85   335.1  752.42
   345.3  753.53   355.4  754.27   365.6   755.7   375.8  758.65   385.9   761.9
   396.1  764.62   416.3  767.23   426.5  769.74   446.8  776.16     528  802.92
   558.4  813.73     599  827.32   619.3  834.62   649.7  846.44   700.5  865.19
#Mann= 3 , 0 , 0
       0      .1       0   215.9    .045       0   230.9      .1       0
Bank Sta=215.9,230.9
XS Rating Curve= 0 ,0
Exp/Cntr=0.3,0.1

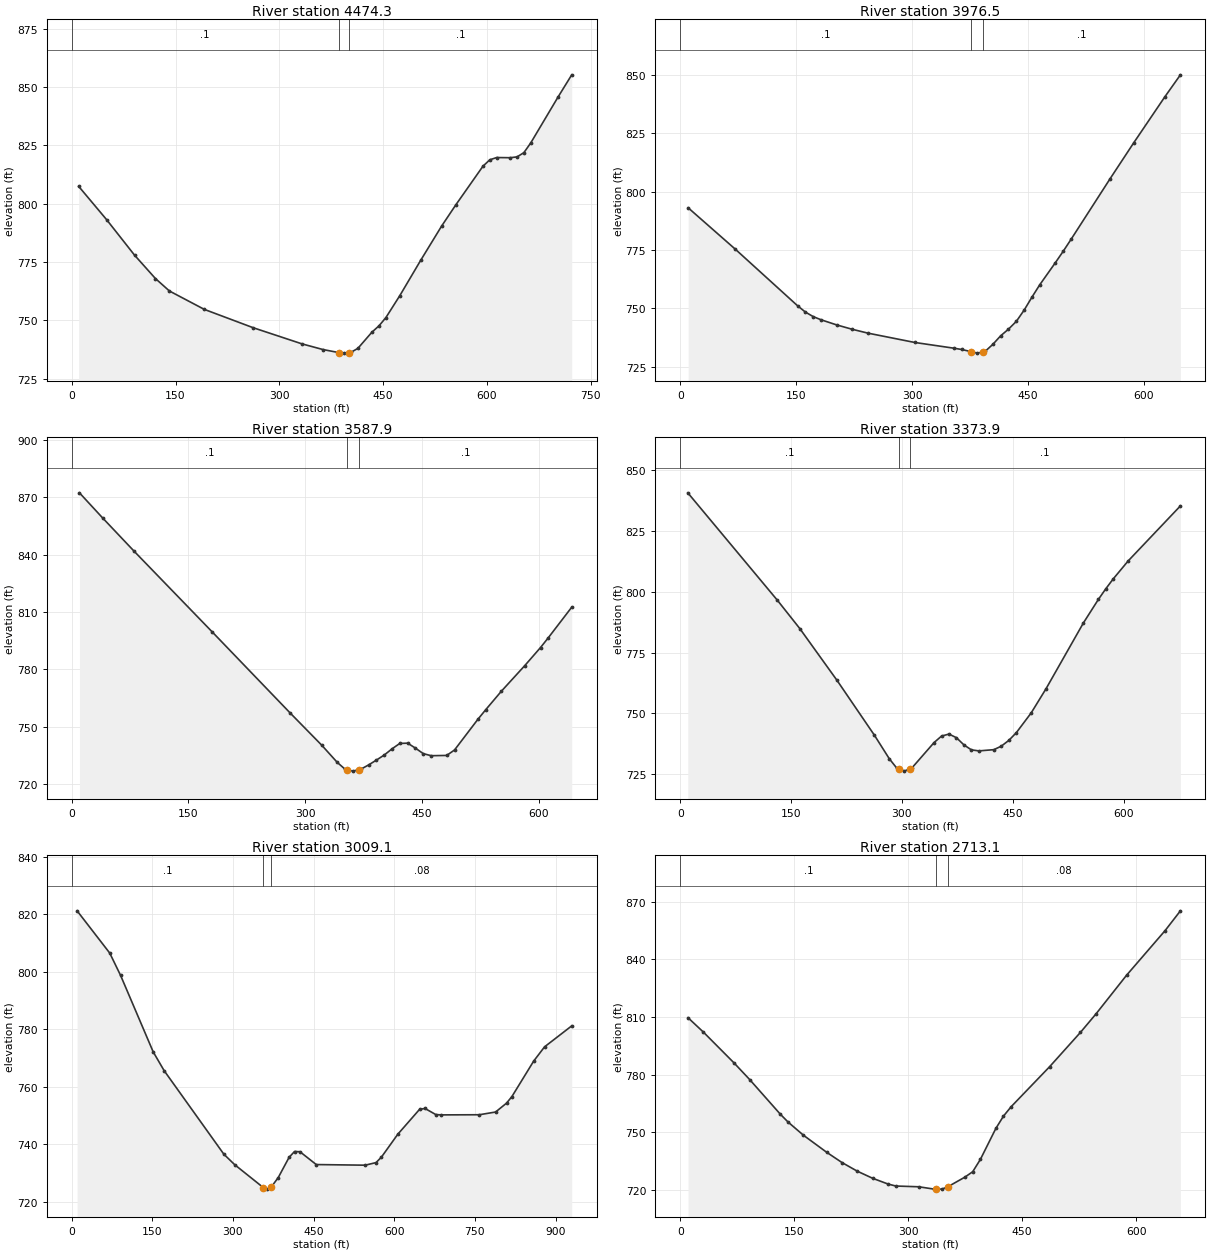
Type RM Length L Ch R = 1 ,4474.3  ,501.6,497.8,493.8
XS GIS Cut Line= 3
     1610037.891      380314.937     1610498.675      380623.761
     1610601.616      380756.114
#Sta/Elev= 30
    10.1  807.43    50.4  793.18    90.8  777.95     121  767.92   141.2  762.58
   191.6   754.7   262.2  746.84   332.8  739.91   363.1  737.48   385.8  736.19
   393.3  735.95   400.8   736.2   403.4  736.28   413.5     738   433.7  744.91
   443.8  747.61   453.8  751.12     474  760.57   504.3  775.78   534.5  790.43
   554.7  799.39   594.2  816.08     604  818.79   613.9  819.77   633.6   819.7
   643.5  820.06   653.3  821.88   663.2  826.04   702.6   845.7   722.4  855.22
#Mann= 3 , 0 , 0
       0      .1       0   385.8    .045       0   400.8      .1       0
Bank Sta=385.8,400.8
XS Rating Curve= 0 ,0
Exp/Cntr=0.3,0.1

Type RM Length L Ch R = 1 ,3976.5  ,397.8,388.6,379.5
XS GIS Cut Line= 2
     1609743.773      380756.114     1610332.009      381025.722
#Sta/Elev= 30
    10.1  793.12    70.8  775.47   151.7  751.13   161.8  748.44   171.9  746.49
     182  745.14   202.2  742.94   222.4  741.06   242.7  739.41   303.3  735.41
   353.9  732.96     364   732.4   376.7  731.45   384.2  730.84   391.7  731.37
   394.3  731.56   404.4  734.61   414.5  738.26   424.6  741.11   434.8  744.46
   444.9  749.28     455  754.84   465.1  760.13   485.3   769.6   495.4  774.47
   505.5  779.55   556.1  805.57   586.4  820.82   626.9  840.64   647.1  850.09
#Mann= 3 , 0 , 0
       0      .1       0   376.7    .045       0   391.7      .1       0
Bank Sta=376.7,391.7
XS Rating Curve= 0 ,0
Exp/Cntr=0.3,0.1

Type RM Length L Ch R = 1 ,3587.9  ,213.7,214,214.3
XS GIS Cut Line= 2
     1609582.009      381256.114     1610224.166       381270.82
#Sta/Elev= 30
      10  872.22    40.1  858.96    80.3  841.69   180.7  799.51     281   757.1
   321.2  740.43   341.2  731.42   351.3  727.85   353.8  727.61   361.3  726.89
   368.8  727.64   371.3  727.88   381.4  730.12   391.4  732.65   401.5   735.3
   411.5  738.54   421.5  741.36   431.6  741.49   441.6  738.89   451.6  736.03
   461.7  734.95   481.7  735.08   491.8  737.95   521.9  754.03   531.9     759
     552  768.65   582.1  782.04   602.2  791.43   612.2  796.54   642.3   812.5
#Mann= 3 , 0 , 0
       0      .1       0   353.8    .045       0   368.8      .1       0
Bank Sta=353.8,368.8
XS Rating Curve= 0 ,0
Exp/Cntr=0.3,0.1

Type RM Length L Ch R = 1 ,3373.9  ,343.7,364.8,385.9
XS GIS Cut Line= 2
     1609626.126      381466.898     1610302.597      381491.408
#Sta/Elev= 30
    10.1  840.52   131.3  796.47   161.7  784.84   212.2  763.54   262.7  741.09
   282.9  731.41     293  727.58   295.6  727.26   303.1  726.36   310.6  727.27
   313.2  727.58   343.5   738.1   353.6  740.75   363.7  741.56   373.8  740.05
   383.9  737.11     394  735.08   404.1  734.66   424.3  735.16   434.4  736.59
   444.5  738.94   454.6  742.06   474.9  750.24   495.1  760.21   545.6  787.16
   565.8  796.77   575.9  801.16     586  805.23   606.2  812.59   676.9  835.16
#Mann= 3 , 0 , 0
       0      .1       0   295.6    .045       0   310.6      .1       0
Bank Sta=295.6,310.6
XS Rating Curve= 0 ,0
Exp/Cntr=0.3,0.1

Type RM Length L Ch R = 1 ,3009.1  ,281.3,296,310.8
XS GIS Cut Line= 2
     1609665.342      381525.722     1610194.754      382290.427
#Sta/Elev= 30
    10.1  821.12    70.8  806.44      91  798.67   151.6  772.11   171.9   765.6
   283.1  736.53   303.3  732.88   356.4  724.95   363.9   724.4   371.4  725.18
   384.2  728.41   404.4  735.45   414.5  737.47   424.6   737.4   454.9  732.94
   545.9  732.72   566.1  733.62   576.2  735.54   606.6  743.48     647  752.11
   657.1  752.44   677.3  750.31   687.5   750.2   758.2  750.25   788.5   751.2
   808.8  754.28   818.9  756.59   859.3  768.89   879.5  773.84   930.1  781.14
#Mann= 3 , 0 , 0
       0      .1       0   356.4    .045       0   371.4     .08       0
Bank Sta=356.4,371.4
XS Rating Curve= 0 ,0
Exp/Cntr=0.3,0.1

Type RM Length L Ch R = 1 ,2713.1  ,458.7,444,429.2
XS GIS Cut Line= 2
     1609655.538      381589.447      1609611.42       382246.31
#Sta/Elev= 30
    10.1  809.67    30.4  802.15    70.9  786.03    91.2  777.48   131.7  759.37
   141.8  755.32   162.1  748.43   192.4  739.63   212.7  734.24     233   729.7
   253.2  726.01   273.5  723.01   283.6  721.99     314  721.59   334.2  720.37
   336.9  720.37   344.4  720.37   351.9  721.55   374.7  726.64   384.9  729.45
     395  735.88   415.3  751.96   425.4  758.42   435.5  763.32   486.2  784.18
   526.7  802.02   546.9  811.52   587.4  831.79   638.1  855.03   658.3  865.35
#Mann= 3 , 0 , 0
       0      .1       0   336.9    .045       0   351.9     .08       0
Bank Sta=336.9,351.9
XS Rating Curve= 0 ,0
Exp/Cntr=0.3,0.1