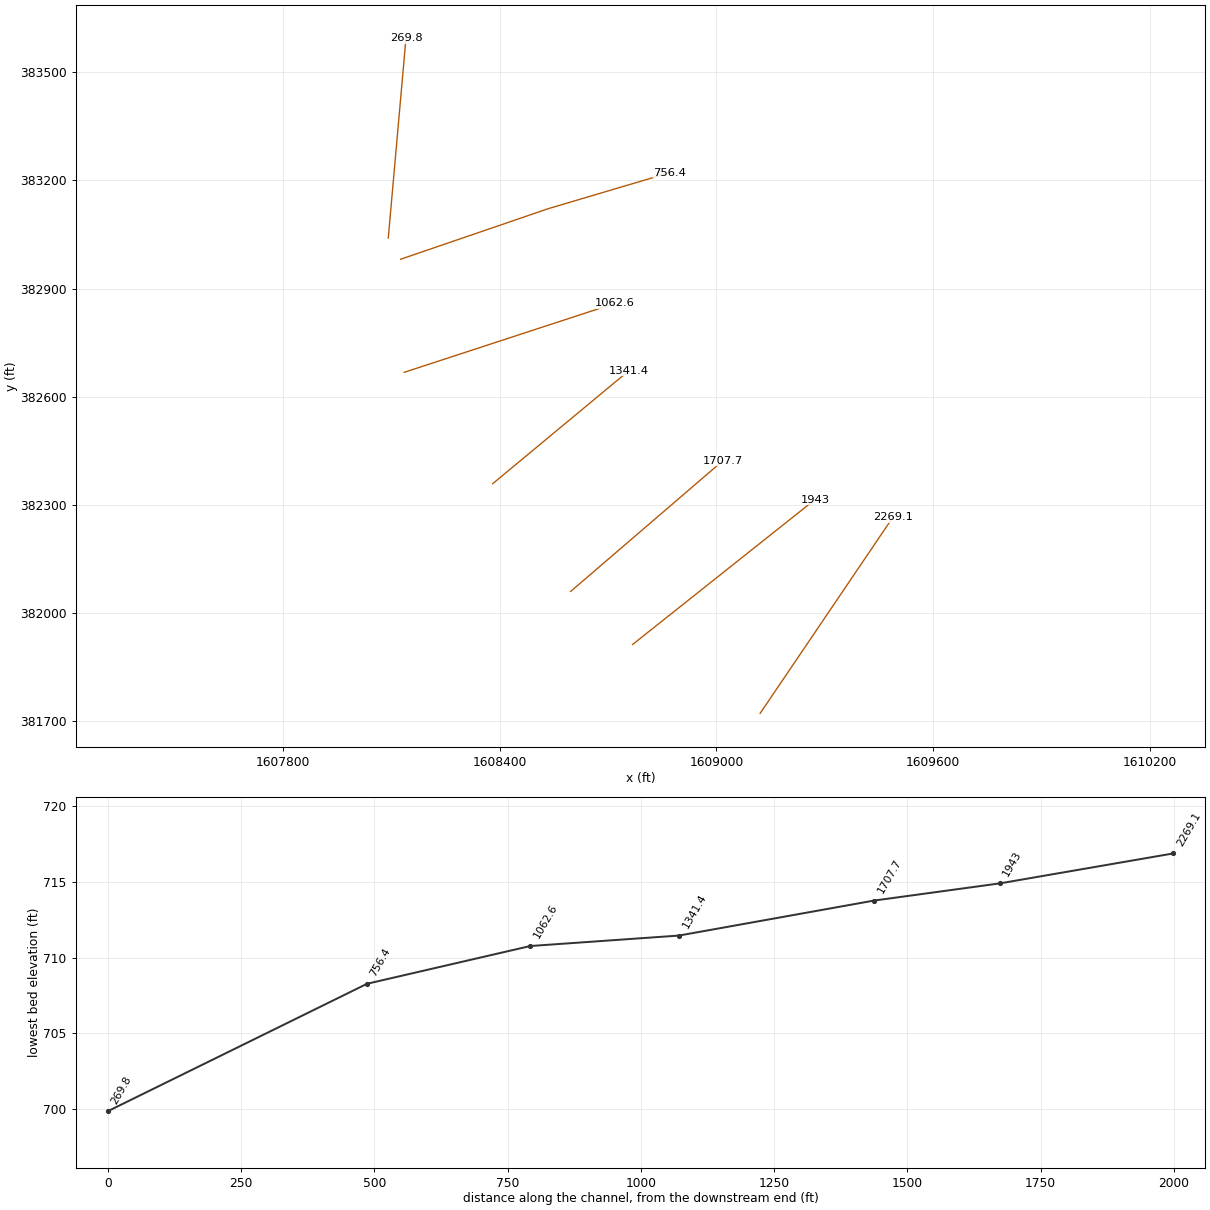
HEC-RAS study TROUGHFK.prj: TROUGHFK

--- TROUGHFK.g01 (geometry) --- (continued)

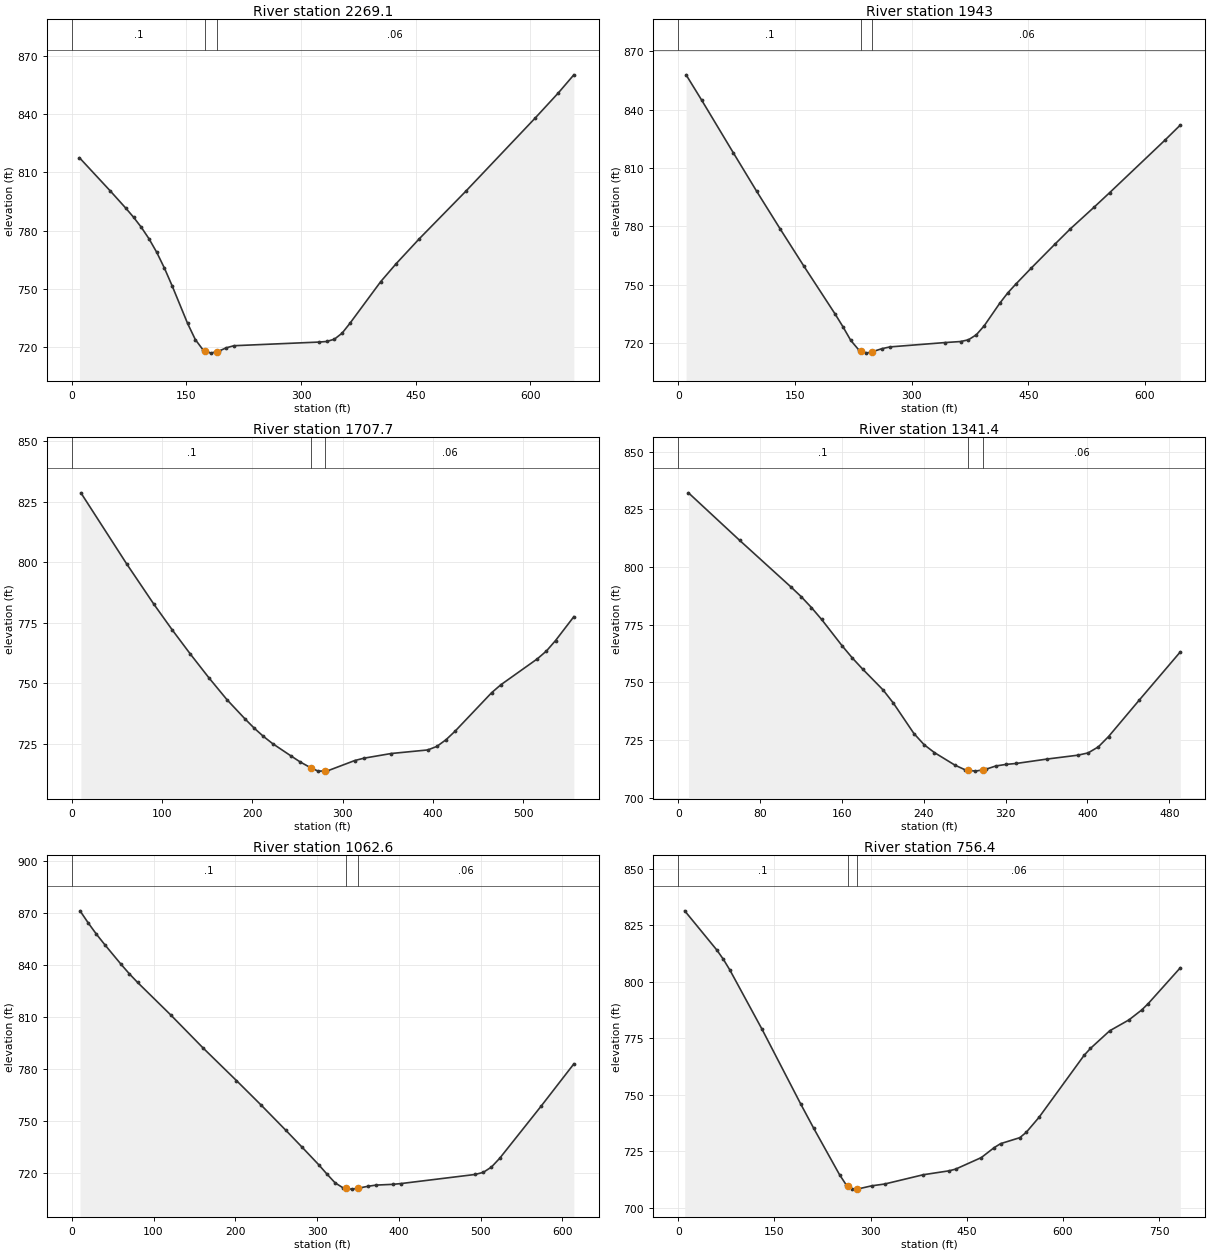
Type RM Length L Ch R = 1 ,2269.1  ,332.9,326.1,319.3
XS GIS Cut Line= 2
     1609121.224        381721.8     1609488.871      382265.918
#Sta/Elev= 30
    10.1  817.54    50.5  800.39    70.7  791.56    80.8  786.91    90.9  781.75
     101  775.81   111.1  768.84   121.2  760.67   131.3  751.53   151.5  732.17
   161.6  723.86   171.7  718.55   174.4   718.1   181.8  716.87   189.4  717.59
     192  717.83   202.1  719.62   212.2  720.69   323.3  722.57   333.4  722.87
   343.5  724.05   353.6  727.17   363.7  732.17   404.1  753.72   424.3  762.97
   454.6  775.82   515.2  800.22   606.2  838.04   636.5     851   656.7  860.28
#Mann= 3 , 0 , 0
       0      .1       0   174.4    .045       0   189.4     .06       0
Bank Sta=174.4,189.4
XS Rating Curve= 0 ,0
Exp/Cntr=0.3,0.1

Type RM Length L Ch R = 1 ,1943    ,234.4,235.3,236.2
XS GIS Cut Line= 2
     1608768.283      381912.977     1609273.185      382314.937
#Sta/Elev= 30
    10.1  857.91    30.3  844.79    70.6  817.98   100.8  798.08   131.1  778.68
   161.3  759.73   201.7  734.97   211.8   728.4   221.8  721.42   231.9  716.63
   234.5  716.19     242  714.89   249.5  715.61   262.2  717.22   272.3  718.09
   342.9  720.32     363  720.85   373.1  721.75   383.2  724.33   393.3  728.93
   413.4  740.58   423.5   745.8   433.6  750.21   453.8   758.6     484   770.8
   504.2  778.82   534.4  789.83   554.6  797.37   625.2  824.17   645.4   832.1
#Mann= 3 , 0 , 0
       0      .1       0   234.5    .045       0   249.5     .06       0
Bank Sta=234.5,249.5
XS Rating Curve= 0 ,0
Exp/Cntr=0.3,0.1

Type RM Length L Ch R = 1 ,1707.7  ,366.7,366.3,365.9
XS GIS Cut Line= 2
     1608596.715      382060.035     1609018.283      382422.781
#Sta/Elev= 30
    10.1   828.7    60.7  799.42      91  782.68   111.2  772.14   131.5  762.05
   151.7  752.41   171.9  743.28   192.1  735.26   202.2  731.48   212.3  728.11
   222.5  725.12   242.7  720.08   252.8  717.61   265.5  714.98     273  713.76
   280.5  713.82   283.1  713.84   313.5  718.14   323.6   719.1   353.9  721.04
   394.4  722.51   404.5  723.98   414.6  726.73   424.7  730.28   465.1  746.14
   475.3  749.42   515.7  760.12   525.8  763.36   535.9  767.68   556.2  777.55
#Mann= 3 , 0 , 0
       0      .1       0   265.5    .045       0   280.5     .06       0
Bank Sta=265.5,280.5
XS Rating Curve= 0 ,0
Exp/Cntr=0.3,0.1

Type RM Length L Ch R = 1 ,1341.4  ,287.4,278.9,270.4
XS GIS Cut Line= 2
     1608381.028      382359.055     1608758.479      382672.781
#Sta/Elev= 30
      10  832.12    60.1  811.49   110.2   791.3   120.2   787.1   130.2  782.39
   140.2   777.2   160.3  765.74   170.3  760.46   180.3  755.68   200.3  746.63
   210.3  740.95   230.4  727.75   240.4  722.89   250.4   719.5   270.4  714.07
   280.5  712.01     283  711.87   290.5  711.45     298  712.03   300.5  712.23
   310.5  713.69   320.5  714.37   330.5  714.78   360.6  716.69   390.6  718.36
   400.7  719.35   410.7  721.98   420.7  726.46   450.7  742.27   490.8  763.15
#Mann= 3 , 0 , 0
       0      .1       0     283    .045       0     298     .06       0
Bank Sta=283,298
XS Rating Curve= 0 ,0
Exp/Cntr=0.3,0.1

Type RM Length L Ch R = 1 ,1062.6  ,305.9,306.2,306.5
XS GIS Cut Line= 2
      1608135.93      382667.879     1608719.264      382859.055
#Sta/Elev= 30
    10.1  871.45    20.1  864.48    30.2  857.93    40.3  851.95    60.4   840.5
    70.4  835.09    80.5   830.1   120.8  811.43     161  792.05   201.3  773.48
   231.5  759.31   261.6   744.8   281.8  734.89   301.9  724.87     312  719.46
     322  714.39   332.1  711.38   334.7  711.22   342.2  710.76   349.7  711.24
   362.3  712.42   372.3   713.1   392.5  713.52   402.5  713.97   493.1  719.22
   503.2  720.45   513.2  723.53   523.3  728.61   573.6   758.5   613.9  783.07
#Mann= 3 , 0 , 0
       0      .1       0   334.7    .045       0   349.7     .06       0
Bank Sta=334.7,349.7
XS Rating Curve= 0 ,0
Exp/Cntr=0.3,0.1

Type RM Length L Ch R = 1 ,756.4   ,460.4,486.5,512.7
XS GIS Cut Line= 3
     1608126.126      382981.604     1608535.276      383121.998
     1608871.224        383221.8
#Sta/Elev= 30
    10.1  831.47    60.4  814.04    70.4     810    80.5  805.28   130.8  778.99
   191.1  745.91   211.3   735.2   251.5  714.69   261.6  710.31   264.1   709.8
   271.6  708.27   279.1  708.27   301.8  709.74   321.9  710.53   382.3  714.65
   422.5  716.38   432.6  717.13   472.6  722.23   492.6  726.62   502.7   728.4
   532.7  731.05   542.7  733.41   562.7  740.07   632.8  767.44   642.8  770.55
   672.9  778.37   702.9  783.19   722.9  787.61     733  790.42     783  806.26
#Mann= 3 , 0 , 0
       0      .1       0   264.1    .045       0   279.1     .06       0
Bank Sta=264.1,279.1
XS Rating Curve= 0 ,0
Exp/Cntr=0.3,0.1

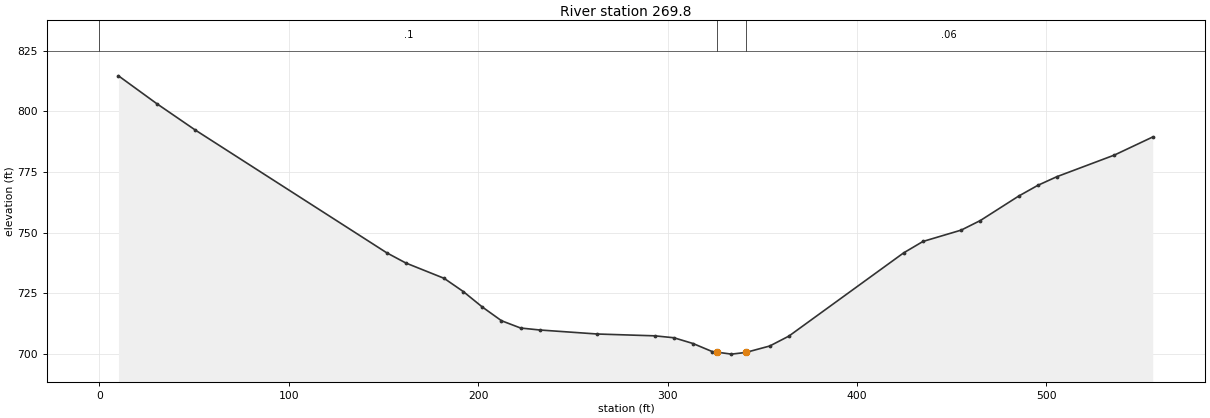
Type RM Length L Ch R = 1 ,269.8   ,287.9,269.8,251.8
XS GIS Cut Line= 2
     1608091.813      383040.428     1608140.832      383594.349
#Sta/Elev= 30
    10.1  814.69    30.3  803.22    50.6  792.35   151.7  741.68   161.8  737.46
     182  731.14   192.1   725.7   202.2  719.29   212.3  713.64   222.4  710.63
   232.5  709.82   262.9  708.16   293.2  707.41   303.3  706.62   313.4  704.24
   323.5  700.93   326.2  700.65   333.7  699.86   341.2  700.54   353.9  703.21
     364  707.29   424.6  741.64   434.8  746.35     455  751.04   465.1  754.99
   485.3  765.06   495.4  769.49   505.5  773.08   535.9  782.01   556.1  789.46
#Mann= 3 , 0 , 0
       0      .1       0   326.2    .045       0   341.2     .06       0
Bank Sta=326.2,341.2
XS Rating Curve= 0 ,0
Exp/Cntr=0.3,0.1

Chan Stop Cuts=-1
Use User Specified Reach Order=0